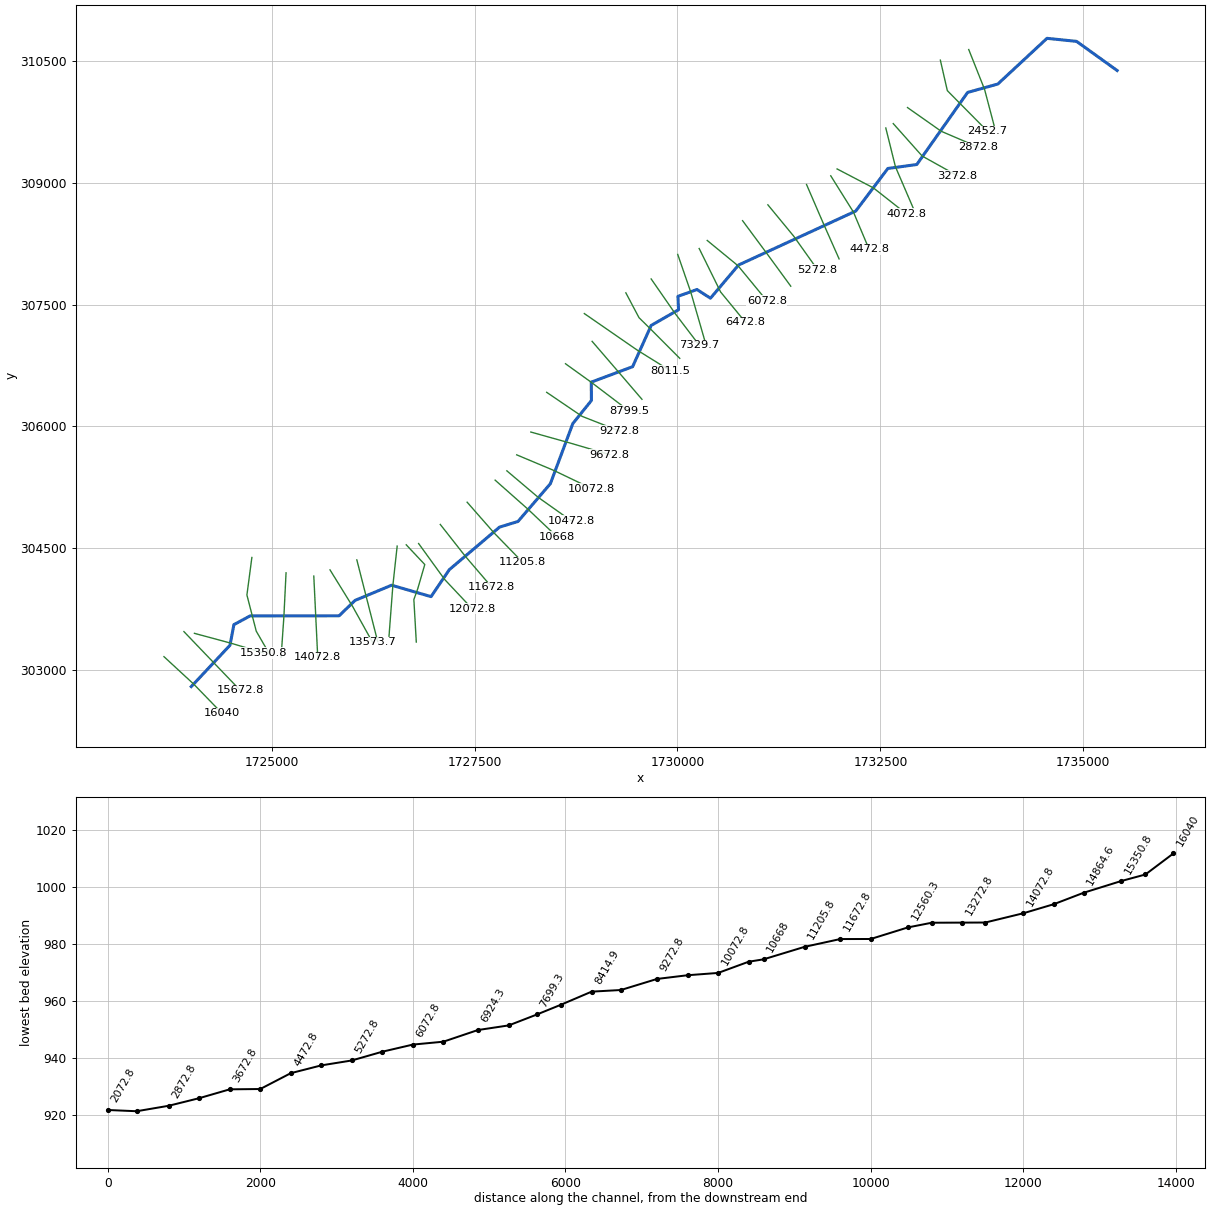
--- LambertRn.prj (project) ---

Proj Title=LambertRn
Current Plan=p01
Geom File=g01
Flow File=f01
Plan File=p01
DSS Export Rating Curves=0
DSS Export Rating Curve Sorted=0
DSS Export Volume Flow Curves=0
DXF OffsetX=0
DXF OffsetY=0
DXF ScaleX=0
DXF ScaleY=0

--- LambertRn.p01 (plan) ---

Plan Title=Floodplain
Program Version=4.00
Geom File=g01
Flow File=f01
K Sum by GR=0
Std Step Tol=0.01
Critical Tol=0.01
Num of Std Step Trials=20
Max Error Tol=0.3
Flow Tol Ratio=0.001
Split Flow NTrial=30
Split Flow Tol=0.02
Split Flow Ratio=0.02
Log Output Level=0
Friction Slope Method=1
Unsteady Friction Slope Method=2
Unsteady Bridges Friction Slope Method=1
Global Log Level=0
CheckData=False
Run HTab=0
Run UNet=0
Run PostProcess=0
UNET Theta=0
UNET Theta Warmup=0
UNET ZTol=0
UNET ZSATol=0
UNET MxIter=0
UNET MaxInSteps=0
UNET DtIC=0
UNET DtMin=0
UNET MaxCRTS=0
UNET WFStab=0
UNET SFStab=0
UNET WFX=0
UNET SFX=0
UNET DSS MLevel=0
UNET DZMax Abort=0
UNET Convert EG Bridges=0
UNET Use Existing IB Tables=0
UNET Froude Limit=0
UNET Froude Power=0
Write IC File=0
Echo Input=False
Echo Output=False
Write Detailed=0

--- LambertRn.f01 (steady flow) ---

Flow Title=NFF Regression Equation
Program Version=4.00
Number of Profiles=1
Profile Names=P100yr
River Rch & RM=LambertRn,Main      ,16040
759.9212
River Rch & RM=LambertRn,Main      ,14864.6
780.4385
River Rch & RM=LambertRn,Main      ,14472.8
1261.920
River Rch & RM=LambertRn,Main      ,12072.8
1394.807
River Rch & RM=LambertRn,Main      ,7699.3
1501.419
River Rch & RM=LambertRn,Main      ,7329.7
1821.769
River Rch & RM=LambertRn,Main      ,3672.8
1924.593
River Rch & RM=LambertRn,Main      ,308.8
2132.070
River Rch & RM=LambertRn,Main      ,72.8
2134.115
Boundary for River Rch & Prof#=LambertRn,Main      ,1
Up Type=0
Dn Type=3
Dn Slope=0.006579

--- LambertRn.g01 (geometry) ---

Geom Title=USGS 3m DEM
Program Version=4.00

River Reach=LambertRn     ,Main
Reach XY= 30
     1724009.359      302790.092     1724486.242      303299.693
     1724534.733      303554.198     1724734.652      303661.778
     1725830.577      303662.816     1726027.405      303852.818
     1726477.445      304040.230     1726964.001      303899.350
     1727188.354      304231.293     1727808.091      304756.711
     1728034.967      304826.215     1728433.755      305291.640
     1728710.804      306033.593     1728939.653      306317.649
     1728937.883      306544.337     1729447.331      306734.682
     1729675.954      307243.320     1730013.222      307436.834
     1730005.992      307602.055     1730240.271      307686.308
     1730406.737      307579.009     1730752.780      307988.401
     1732196.274      308653.501     1732592.401      309178.810
     1732949.088      309227.729     1733574.937      310116.575
     1733947.082      310220.032     1734553.193      310783.486
     1734917.807      310745.896     1735417.294      310386.607

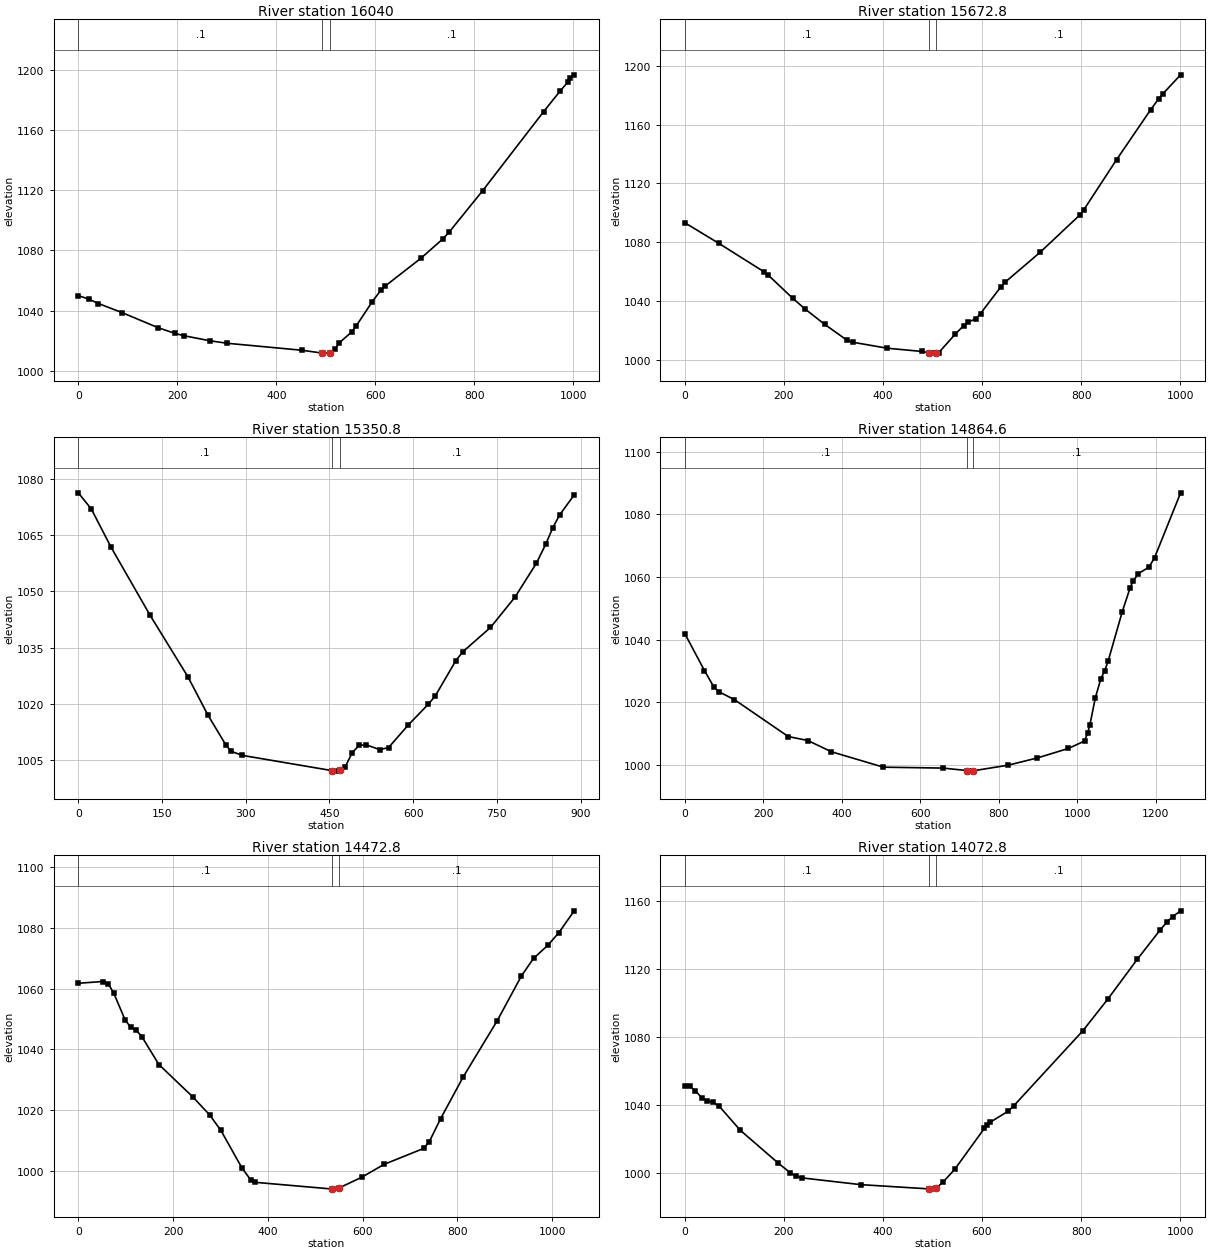
Type RM Length L Ch R = 1 ,16040,368.483,367.145,366.972
XS GIS Cut Line= 3
     1723672.809      303159.430     1724041.026      302819.092
     1724389.329      302459.893
#Sta/Elev= 30
       0 1049.97    20.9 1047.70    40.7 1044.70    89.2 1038.58   160.8 1028.72
   195.8 1024.84   213.3 1023.35   267.0 1019.93   300.7 1018.34   451.3 1013.71
   492.7 1011.82   493.4 1011.79   507.7 1011.83   510.0 1011.84   518.5 1014.38
   527.0 1018.55   552.0 1025.76   561.2 1029.70   594.0 1046.02   612.3 1053.98
   619.2 1056.10   692.1 1074.75   736.8 1087.68   748.8 1091.95   817.0 1119.64
   940.1 1172.09   973.2 1185.67   989.7 1191.91   992.7 1194.09  1001.8 1196.52
#Mann= 3 , 0 , 0
       0     0.1       0   492.7   0.045       0   507.7     0.1       0
Bank Sta=   492.7,   507.7
Exp/Cntr=0.3,0.1

Type RM Length L Ch R = 1 ,15672.8,309.628,322.1,334.034
XS GIS Cut Line= 3
     1723918.960      303468.124     1724265.171      303106.684
     1724611.381      302745.244
#Sta/Elev= 30
       0 1093.21    69.0 1079.11   159.4 1059.89   167.9 1057.71   218.1 1041.68
   243.3 1034.32   282.7 1023.90   327.3 1013.22   339.6 1011.77   408.2 1007.75
   478.5 1005.52     493 1004.64   496.4 1004.38     508 1004.42   512.8 1004.73
   545.5 1017.15   562.7 1023.02   570.8 1025.30   587.6 1027.78   597.0 1031.33
   638.0 1049.52   646.4 1052.63   717.2 1073.02   797.5 1098.50   805.9 1102.20
   871.6 1136.13   940.3 1170.10   956.7 1177.65   965.5 1181.17  1001.0 1193.97
#Mann= 3 , 0 , 0
       0     0.1       0     493   0.045       0     508     0.1       0
Bank Sta=     493,     508
Exp/Cntr=0.3,0.1

Type RM Length L Ch R = 1 ,15350.8,510.756,486.131,462.043
XS GIS Cut Line= 3
     1724048.370      303446.744     1724496.988      303325.780
     1724902.997      303204.314
#Sta/Elev= 30
       0 1076.26    23.2 1071.96    58.8 1061.71   128.6 1043.59   196.4 1027.18
   232.2 1016.99   264.2 1009.05   273.9 1007.32   293.7 1006.24   453.7 1002.20
   465.9 1002.04   468.7 1002.23   478.3 1003.24   490.6 1006.91   503.0 1008.89
   515.4 1009.07   540.2 1007.77   556.0 1008.34   591.5 1014.40   627.0 1019.87
   639.6 1022.10   676.5 1031.54   688.9 1033.87   738.5 1040.35   782.3 1048.43
   820.5 1057.42   837.6 1062.60   850.0 1066.91   862.4 1070.38   888.4 1075.69
#Mann= 3 , 0 , 0
       0     0.1       0   453.7   0.045       0   468.7     0.1       0
Bank Sta=   453.7,   468.7
Exp/Cntr=0.3,0.1

Type RM Length L Ch R = 1 ,14864.6,398.595,391.769,384.5
XS GIS Cut Line= 4
     1724756.070      304382.180     1724694.989      303919.401
     1724809.943      303473.681     1724977.935      303182.679
#Sta/Elev= 30
       0 1041.89    50.1 1030.08    74.0 1024.85    86.0 1023.36   126.0 1020.84
   263.5 1009.02   313.6 1007.74   373.4 1004.16   506.1  999.23   658.1  998.94
   719.3  998.15   726.3  997.97   734.3  998.07   823.8  999.87   898.4 1002.19
   977.3 1005.22  1018.4 1007.59  1026.2 1010.14  1032.1 1012.82  1045.8 1021.38
  1059.6 1027.36  1069.6 1030.04  1078.3 1033.06  1114.4 1048.88  1134.6 1056.59
  1141.8 1058.60  1155.5 1061.08  1182.1 1063.08  1196.6 1066.12  1263.1 1086.86
#Mann= 3 , 0 , 0
       0     0.1       0   719.3   0.045       0   734.3     0.1       0
Bank Sta=   719.3,   734.3
Exp/Cntr=0.3,0.1

Type RM Length L Ch R = 1 ,14472.8,397.736,400,402.708
XS GIS Cut Line= 3
     1725177.261      304193.624     1725150.412      303650.678
     1725115.792      303149.002
#Sta/Elev= 30
       0 1061.80    51.1 1062.36    63.0 1061.68    74.9 1058.49    98.7 1049.73
   110.6 1047.27   122.4 1046.29   134.3 1044.15   170.0 1035.01   241.3 1024.39
   277.0 1018.42   300.8 1013.31   345.5 1000.88   363.9  996.97   372.1  996.20
   536.1  993.97   538.0  993.94   551.1  994.38   598.0  997.85   645.6 1002.12
   728.9 1007.36   740.8 1009.60   764.6 1017.15   812.2 1030.89   884.1 1049.45
   935.2 1064.21   960.7 1069.99   990.7 1074.27  1014.5 1078.52  1046.5 1085.67
#Mann= 3 , 0 , 0
       0     0.1       0   536.1   0.045       0   551.1     0.1       0
Bank Sta=   536.1,   551.1
Exp/Cntr=0.3,0.1

Type RM Length L Ch R = 1 ,14072.8,488.102,499.101,510.1
XS GIS Cut Line= 3
     1725519.134      304152.880     1725543.338      303652.966
     1725567.542      303153.051
#Sta/Elev= 30
       0 1051.51     9.9 1051.15    21.3 1048.49    34.1 1044.46    43.9 1042.61
    57.9 1041.69    69.8 1039.33   112.0 1025.32   188.6 1006.04   212.4 1000.49
   224.3  998.31   236.2  997.36   355.0  993.39     493  990.89   497.4  990.75
     508  991.50   521.5  994.92   545.2 1002.47   604.7 1026.40   610.8 1028.38
   616.5 1030.04   652.2 1036.41   664.1 1039.68   803.6 1083.75   854.3 1102.46
   913.7 1125.81   960.1 1143.11   973.1 1147.50   985.0 1150.81  1001.0 1154.19
#Mann= 3 , 0 , 0
       0     0.1       0     493   0.045       0     508     0.1       0
Bank Sta=     493,     508
Exp/Cntr=0.3,0.1

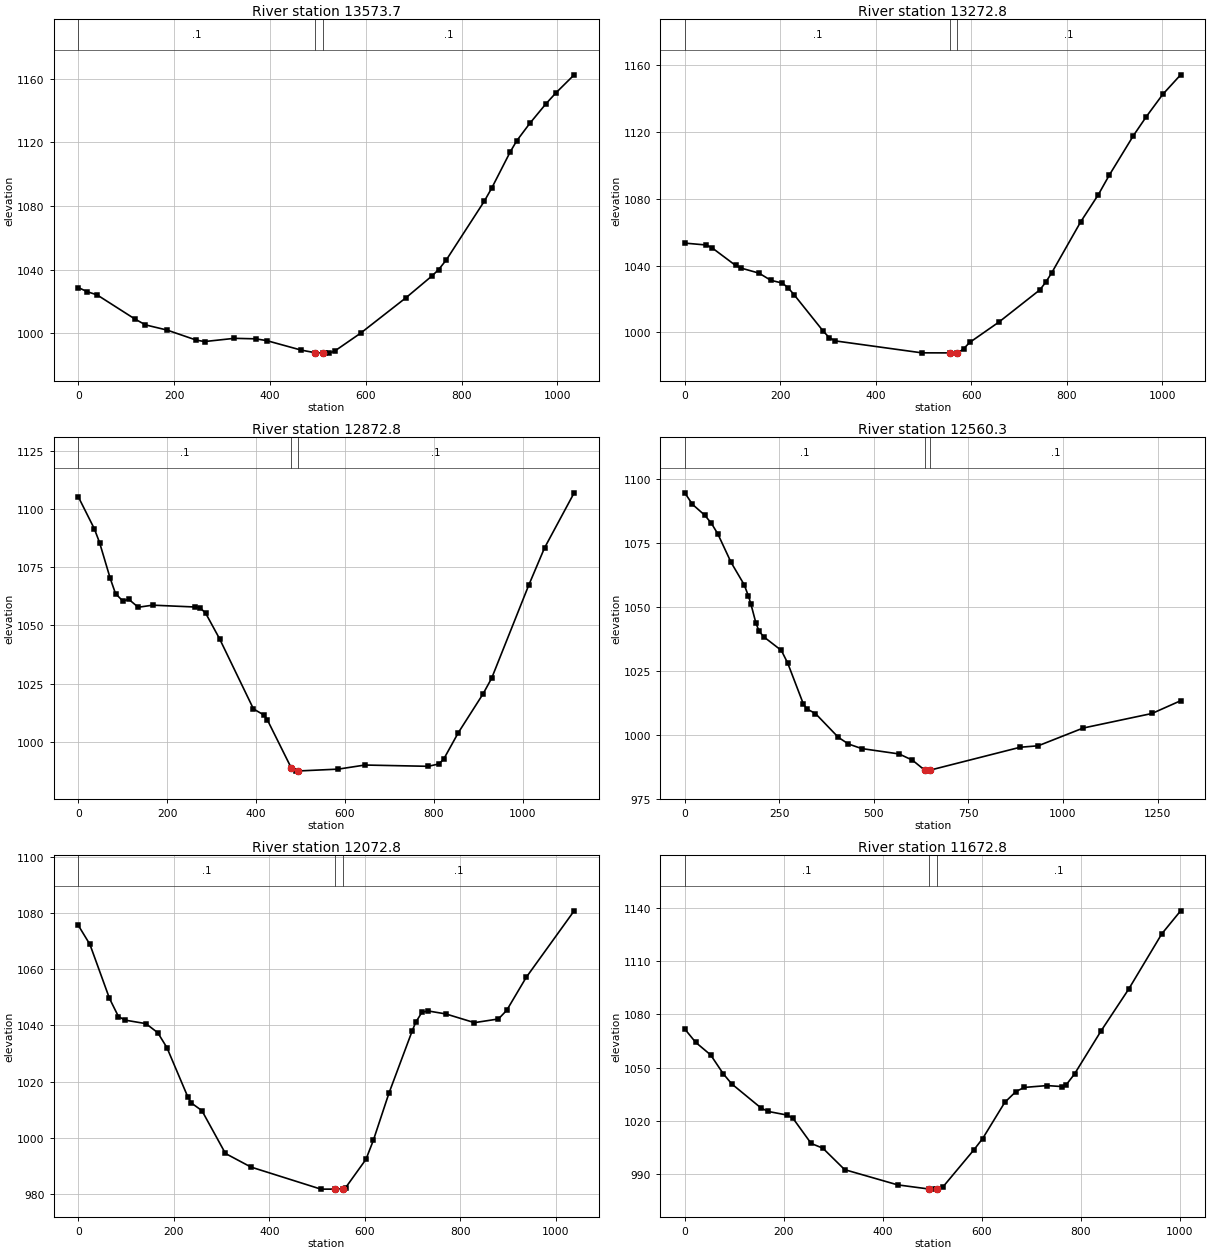
Type RM Length L Ch R = 1 ,13573.7,224.2,300.899,281.675
XS GIS Cut Line= 3
     1725718.749      304229.724     1725998.595      303776.355
     1726242.337      303337.306
#Sta/Elev= 30
       0 1028.74    18.7 1026.11    39.1 1024.14   117.4 1009.08   140.0 1005.27
   185.2 1002.00   246.2  995.69   263.4  994.76   325.7  996.80   370.0  996.48
   392.8  995.39   465.2  989.39   494.7  987.73   509.7  987.50   515.8  987.49
   524.2  987.57   534.9  988.74   589.2 1000.04   684.3 1022.42   738.6 1036.15
   752.2 1040.09   768.1 1046.11   847.2 1082.95   862.7 1091.18   901.5 1114.06
   915.1 1121.06   942.3 1131.99   976.2 1144.36   996.6 1151.11  1035.0 1162.56
#Mann= 3 , 0 , 0
       0     0.1       0   494.7   0.045       0   509.7     0.1       0
Bank Sta=   494.7,   509.7
Exp/Cntr=0.3,0.1

Type RM Length L Ch R = 1 ,13272.8,489.741,400,390.623
XS GIS Cut Line= 3
     1726049.350      304352.499     1726188.734      303806.843
     1726306.151      303346.344
#Sta/Elev= 30
       0 1053.46    45.1 1052.31    57.4 1050.56   106.4 1040.05   118.6 1038.41
   155.4 1035.44   179.9 1031.18   204.4 1029.46   216.7 1026.54   228.9 1022.50
   290.2 1000.54   302.5  996.77   314.7  994.81   496.4  987.63   555.7  987.60
   570.7  987.47   572.0  987.46   584.3  990.19   596.5  993.84   657.8 1006.08
   743.6 1025.41   755.8 1029.96   768.1 1035.47   829.3 1066.31   866.1 1082.53
   888.6 1094.04   939.6 1117.97   966.7 1129.37  1000.9 1142.65  1038.4 1154.40
#Mann= 3 , 0 , 0
       0     0.1       0   555.7   0.045       0   570.7     0.1       0
Bank Sta=   555.7,   570.7
Exp/Cntr=0.3,0.1

Type RM Length L Ch R = 1 ,12872.8,316.395,312.528,306.714
XS GIS Cut Line= 3
     1726546.354      304522.541     1726493.507      304038.477
     1726445.732      303411.237
#Sta/Elev= 30
       0 1105.26    35.9 1091.60    47.8 1085.62    71.7 1070.28    83.7 1063.70
   100.4 1060.46   113.3 1061.29   134.8 1057.83   167.3 1058.73   262.8 1057.94
   274.7 1057.49   286.7 1055.23   317.8 1044.33   394.2 1014.14   418.1 1011.48
   425.5 1009.42   479.4  988.74   489.7  987.42   494.4  987.48   585.0  988.28
   645.1  990.04   787.4  989.49   811.2  990.49   822.1  992.48   855.3 1003.95
   910.7 1020.53   930.3 1027.34  1013.6 1067.24  1049.3 1083.33  1116.0 1107.00
#Mann= 3 , 0 , 0
       0     0.1       0   479.4   0.045       0   494.4     0.1       0
Bank Sta=   479.4,   494.4
Exp/Cntr=0.3,0.1

Type RM Length L Ch R = 1 ,12560.3,467.842,487.472,511.946
XS GIS Cut Line= 5
     1726658.265      304538.281     1726886.513      304295.248
     1726799.740      303995.997     1726752.030      303863.504
     1726782.034      303339.219
#Sta/Elev= 30
       0 1094.74    20.1 1090.25    53.1 1085.93    70.4 1082.78    87.3 1078.66
   122.4 1067.49   157.1 1058.74   168.3 1054.29   174.5 1051.37   188.1 1043.72
   196.5 1040.52   209.2 1038.31   255.3 1033.03   272.1 1028.07   313.2 1012.17
   322.5 1010.15   345.5 1008.31   405.9  999.01   432.6  996.40   467.4  994.61
   566.6  992.50   602.0  990.05   634.1  986.18   640.7  985.77   649.1  986.18
   886.8  995.12   934.4  995.69  1053.3 1002.64  1235.2 1008.34  1311.0 1013.33
#Mann= 3 , 0 , 0
       0     0.1       0   634.1   0.045       0   649.1     0.1       0
Bank Sta=   634.1,   649.1
Exp/Cntr=0.3,0.1

Type RM Length L Ch R = 1 ,12072.8,398.12,400,398.984
XS GIS Cut Line= 3
     1726810.740      304554.075     1727130.953      304111.674
     1727468.115      303752.825
#Sta/Elev= 30
       0 1075.61    24.3 1068.82    65.2 1049.62    84.0 1043.16    97.6 1041.89
   141.6 1040.63   166.4 1037.39   185.6 1032.07   229.5 1014.46   237.0 1012.33
   258.8 1009.66   308.1  994.40   361.4  989.57   508.0  981.70   538.6  981.70
   553.6  981.84   559.9  982.24   602.4  992.30   617.8  999.03   650.4 1015.78
   699.2 1038.01   706.5 1041.06   719.5 1044.63   731.8 1045.17   769.9 1044.08
   829.6 1040.98   879.8 1042.29   897.2 1045.36   937.9 1057.06  1038.5 1080.80
#Mann= 3 , 0 , 0
       0     0.1       0   538.6   0.045       0   553.6     0.1       0
Bank Sta=   538.6,   553.6
Exp/Cntr=0.3,0.1

Type RM Length L Ch R = 1 ,11672.8,465.799,467.078,468.556
XS GIS Cut Line= 3
     1727077.742      304789.133     1727387.451      304395.270
     1727713.235      304015.443
#Sta/Elev= 30
       0 1071.77    22.0 1064.28    52.2 1057.21    77.7 1046.61    94.6 1040.95
   153.8 1027.38   167.7 1025.44   206.1 1023.39   218.4 1021.58   255.2 1007.38
   278.8 1004.73   322.9  992.64   429.8  984.08   493.5  981.73   505.5  981.68
   508.5  981.72   521.1  982.84   583.7 1003.73   601.5 1010.12   646.3 1030.53
   668.8 1036.61   685.7 1038.92   731.6 1039.96   761.5 1039.40   769.9 1040.24
   787.1 1046.48   841.0 1070.85   896.2 1094.11   963.5 1125.41  1001.4 1138.31
#Mann= 3 , 0 , 0
       0     0.1       0   493.5   0.045       0   508.5     0.1       0
Bank Sta=   493.5,   508.5
Exp/Cntr=0.3,0.1

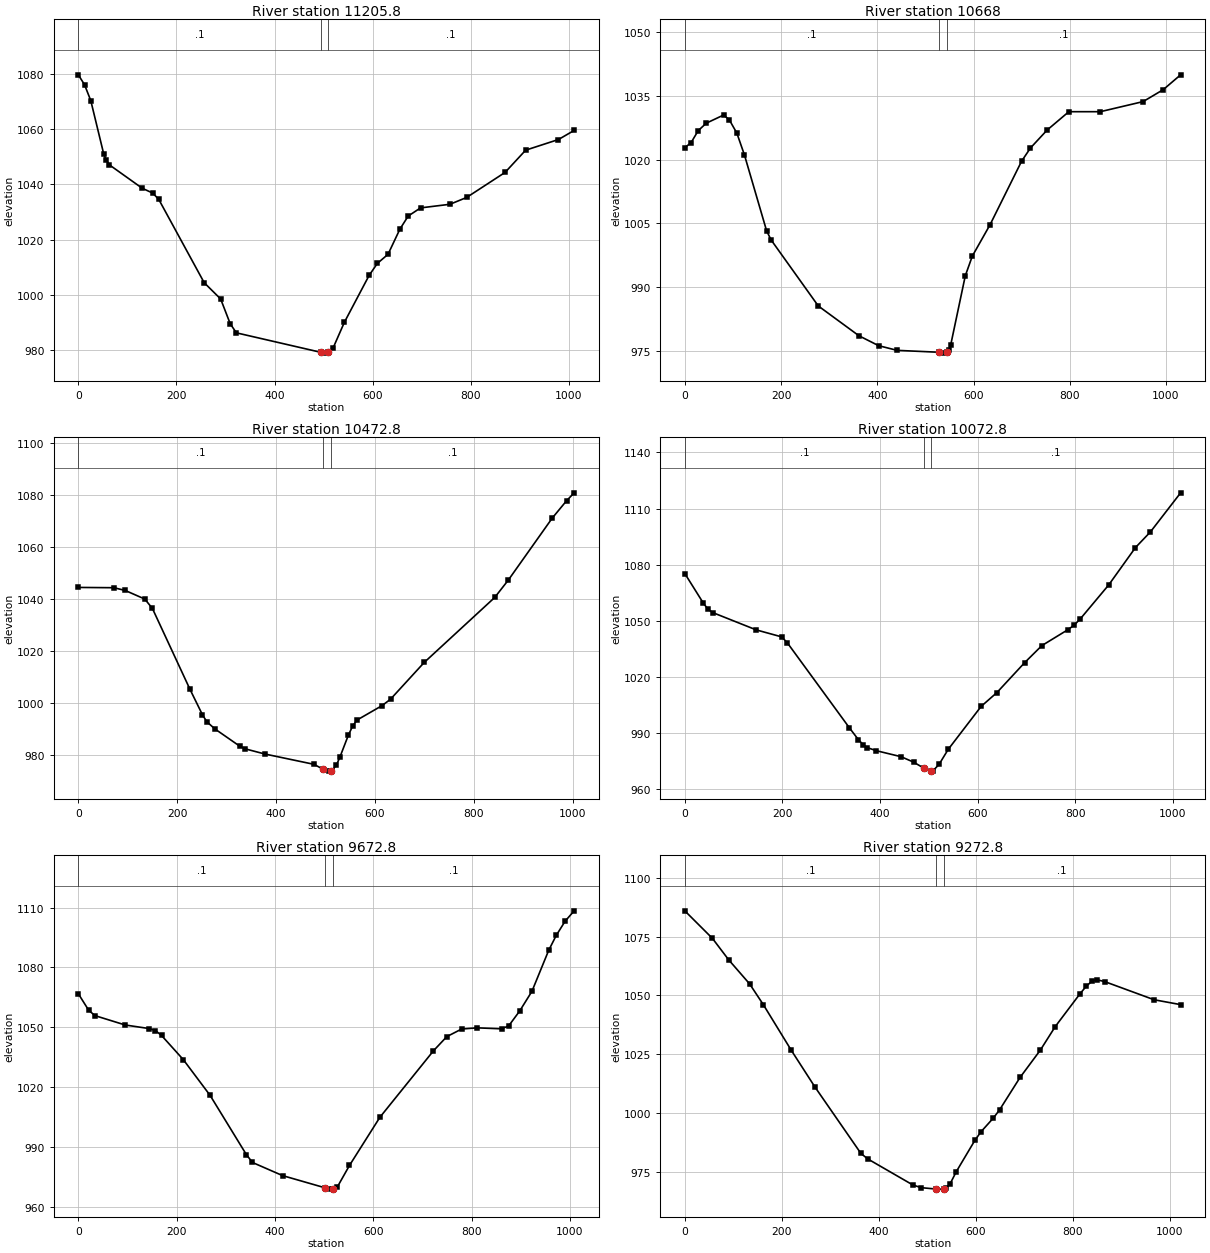
Type RM Length L Ch R = 1 ,11205.8,534.696,537.799,538.987
XS GIS Cut Line= 3
     1727408.325      305064.008     1727739.566      304685.949
     1728094.162      304321.794
#Sta/Elev= 30
       0 1079.62    12.6 1076.05    25.4 1070.28    52.0 1050.81    57.0 1048.80
    63.1 1047.08   130.4 1038.57   151.7 1036.84   164.0 1034.55   256.6 1004.42
   290.2  998.52   309.6  989.59   322.2  986.28   494.2  979.24   502.4  978.94
   509.2  979.35   519.4  980.79   542.5  990.13   592.9 1007.07   609.7 1011.41
   631.4 1014.69   655.6 1023.79   672.6 1028.54   697.7 1031.48   757.7 1032.79
   791.7 1035.26   870.0 1044.31   912.0 1052.36   978.9 1056.22  1010.9 1059.51
#Mann= 3 , 0 , 0
       0     0.1       0   494.2   0.045       0   509.2     0.1       0
Bank Sta=   494.2,   509.2
Exp/Cntr=0.3,0.1

Type RM Length L Ch R = 1 ,10668,194.684,195.123,198.269
XS GIS Cut Line= 3
     1727753.397      305335.676     1728155.021      304980.013
     1728513.549      304640.252
#Sta/Elev= 30
       0 1022.80    13.0 1023.99    27.9 1026.81    44.6 1028.56    80.5 1030.47
    92.3 1029.39   108.2 1026.22   124.0 1021.08   170.0 1003.28   179.3 1001.15
   277.4  985.63   361.9  978.63   402.8  976.30   441.2  975.20   529.2  974.75
   536.3  974.55   544.2  974.88   549.3  975.24   552.7  976.53   582.9  992.71
   597.5  997.34   634.5 1004.74   699.9 1019.63   718.3 1022.73   752.8 1026.93
   798.1 1031.26   863.5 1031.26   952.4 1033.63   994.3 1036.44  1030.4 1039.92
#Mann= 3 , 0 , 0
       0     0.1       0   529.2   0.045       0   544.2     0.1       0
Bank Sta=   529.2,   544.2
Exp/Cntr=0.3,0.1

Type RM Length L Ch R = 1 ,10472.8,393.14,400,403.781
XS GIS Cut Line= 3
     1727898.093      305450.528     1728281.744      305125.325
     1728689.711      304836.131
#Sta/Elev= 30
       0 1044.37    72.1 1044.26    94.9 1043.20   134.4 1039.90   149.8 1036.30
   225.7 1005.23   251.0  995.41   260.1  992.67   276.3  989.94   326.8  983.27
   336.7  982.32   377.4  980.29   476.8  976.32   495.4  974.41   507.6  973.71
   510.4  973.76   512.3  973.79   522.1  976.03   529.3  979.18   546.3  987.57
   554.8  990.99   563.4  993.32   614.5  998.92   631.5 1001.37   699.6 1015.50
   842.3 1040.51   869.9 1047.22   958.7 1071.05   987.8 1077.75  1003.0 1080.76
#Mann= 3 , 0 , 0
       0     0.1       0   495.4   0.045       0   510.4     0.1       0
Bank Sta=   495.4,   510.4
Exp/Cntr=0.3,0.1

Type RM Length L Ch R = 1 ,10072.8,397.261,400,403.591
XS GIS Cut Line= 3
     1728019.197      305647.770     1728477.591      305455.158
     1728945.492      305230.350
#Sta/Elev= 30
       0 1075.32    38.2 1059.42    47.3 1056.31    57.1 1054.46   146.5 1045.20
   198.7 1041.46   210.5 1038.18   337.4  992.89   355.6  986.65   366.2  983.72
   373.7  982.37   391.9  980.72   443.4  977.47   469.2  974.54   489.7  971.40
   504.7  970.03   508.1  969.77   521.2  973.39   539.9  981.38   607.4 1004.34
   639.8 1011.75   696.3 1027.63   731.8 1036.80   784.7 1045.22   797.8 1047.67
   811.0 1051.19   868.9 1069.22   923.7 1089.17   954.4 1097.54  1016.3 1118.41
#Mann= 3 , 0 , 0
       0     0.1       0   489.7   0.045       0   504.7     0.1       0
Bank Sta=   489.7,   504.7
Exp/Cntr=0.3,0.1

Type RM Length L Ch R = 1 ,9672.8,407.502,400,397.998
XS GIS Cut Line= 3
     1728193.732      305928.764     1728684.817      305791.122
     1729163.443      305650.621
#Sta/Elev= 30
       0 1066.82    21.0 1058.58    33.7 1055.87    95.3 1051.17   144.7 1049.36
   157.0 1048.35   169.3 1045.92   213.6 1033.81   268.0 1015.95   341.9  986.25
   354.3  982.31   415.6  975.73   502.5  969.58   514.6  968.96   517.5  969.11
   527.0  970.06   551.7  980.84   613.6 1004.96   722.6 1038.26   749.7 1045.35
   780.0 1049.16   811.5 1049.74   861.0 1049.25   875.6 1050.72   898.2 1058.26
   922.9 1068.04   956.9 1088.52   972.4 1096.06   990.4 1103.15  1008.8 1108.35
#Mann= 3 , 0 , 0
       0     0.1       0   502.5   0.045       0   517.5     0.1       0
Bank Sta=   502.5,   517.5
Exp/Cntr=0.3,0.1

Type RM Length L Ch R = 1 ,9272.8,473.556,473.357,467.378
XS GIS Cut Line= 3
     1728388.701      306418.556     1728824.127      306122.534
     1729286.151      305941.428
#Sta/Elev= 30
       0 1085.92    57.0 1074.21    90.6 1065.08   133.7 1054.87   161.9 1046.08
   219.8 1026.61   268.2 1011.14   363.4  982.80   377.7  980.46   470.1  969.47
   487.2  968.29     519  967.68     534  967.66   539.4  968.13   547.4  969.97
   560.1  975.11   598.4  988.39   611.1  992.06   636.6  997.89   649.4 1001.37
   691.5 1015.10   733.5 1026.75   764.2 1036.74   815.2 1050.66   827.9 1053.82
   840.7 1056.19   850.9 1056.60   866.2 1055.84   968.2 1048.13  1022.8 1046.06
#Mann= 3 , 0 , 0
       0     0.1       0     519   0.045       0     534     0.1       0
Bank Sta=     519,     534
Exp/Cntr=0.3,0.1

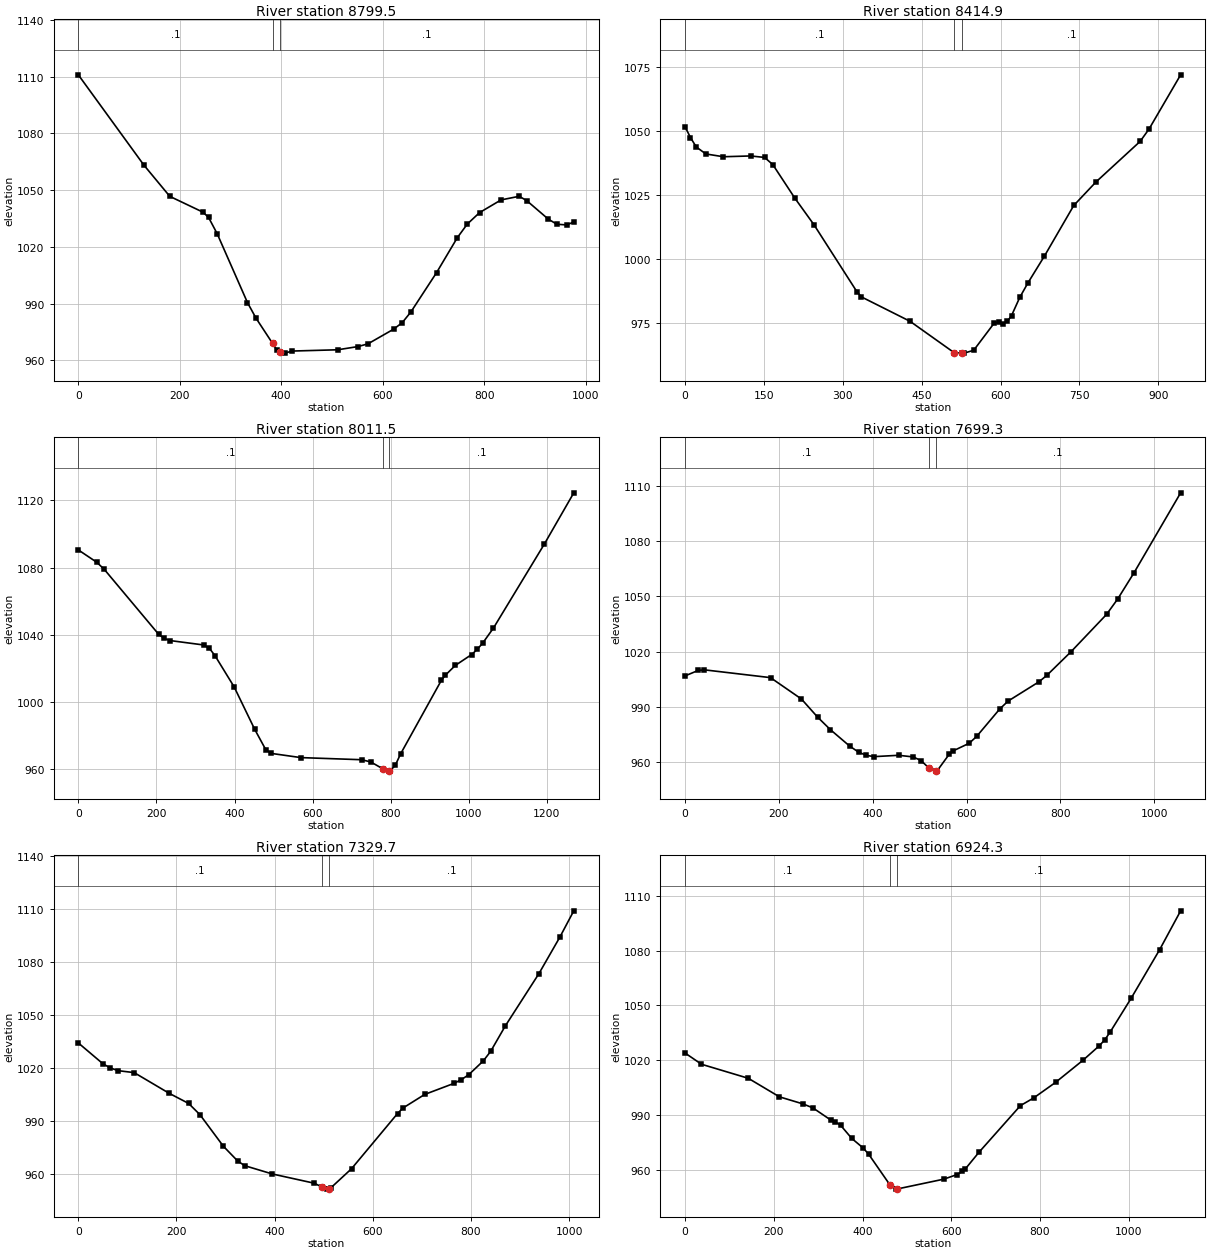
Type RM Length L Ch R = 1 ,8799.5,389.483,384.607,380.287
XS GIS Cut Line= 3
     1728620.254      306770.971     1728938.952      306541.826
     1729404.020      306188.164
#Sta/Elev= 30
       0 1111.03   129.2 1063.29   180.3 1046.73   245.8 1038.35   256.8 1035.57
   273.8 1026.93   333.5  990.50   350.4  982.24   382.9  968.95   392.0  965.22
   397.9  964.40   406.9  963.77   421.8  964.87   511.3  965.54   551.1  967.23
   571.0  968.68   621.7  976.46   638.6  979.90   655.6  985.53   706.4 1006.42
   747.2 1024.86   766.8 1032.05   791.1 1038.14   833.5 1044.85   869.3 1046.76
   884.2 1044.42   926.7 1034.64   943.4 1031.97   963.0 1031.60   976.8 1033.19
#Mann= 3 , 0 , 0
       0     0.1       0   382.9   0.045       0   397.9     0.1       0
Bank Sta=   382.9,   397.9
Exp/Cntr=0.3,0.1

Type RM Length L Ch R = 1 ,8414.9,397.721,403.421,409.871
XS GIS Cut Line= 3
     1728948.493      307047.145     1729307.708      306629.792
     1729562.741      306332.323
#Sta/Elev= 30
       0 1051.46    10.1 1047.30    21.1 1043.65    39.3 1040.92    72.8 1039.83
   124.6 1040.14   151.1 1039.56   166.7 1036.77   208.8 1023.62   245.1 1013.27
   326.7  987.15   335.1  985.15   427.7  975.62     512  963.32   527.0  963.20
   530.7  963.19   548.9  964.31   587.7  974.87   596.1  975.34   605.3  974.75
   612.9  975.56   620.9  977.87   636.5  984.95   652.2  990.66   683.5 1001.10
   739.2 1020.81   781.3 1029.96   865.5 1045.83   882.4 1050.65   942.5 1071.80
#Mann= 3 , 0 , 0
       0     0.1       0     512   0.045       0     527     0.1       0
Bank Sta=     512,     527
Exp/Cntr=0.3,0.1

Type RM Length L Ch R = 1 ,8011.5,316.009,312.148,307.436
XS GIS Cut Line= 3
     1728852.328      307389.793     1729506.603      306937.420
     1729908.565      306687.327
#Sta/Elev= 30
       0 1090.52    47.1 1083.17    66.3 1078.97   205.8 1040.16   220.3 1037.73
   234.7 1036.46   321.3 1033.81   335.7 1031.82   350.2 1027.37   399.1 1008.79
   451.2  983.72   480.1  971.33   494.5  969.13   569.8  966.64   725.5  965.37
   749.0  964.04   780.3  959.88   795.3  958.71   797.6  958.57   811.6  962.02
   825.5  968.93   929.5 1012.64   939.3 1015.66   965.4 1021.61  1007.3 1028.13
  1021.3 1031.13  1035.3 1034.86  1063.2 1043.96  1193.3 1093.97  1268.8 1124.57
#Mann= 3 , 0 , 0
       0     0.1       0   780.3   0.045       0   795.3     0.1       0
Bank Sta=   780.3,   795.3
Exp/Cntr=0.3,0.1

Type RM Length L Ch R = 1 ,7699.3,373.841,369.643,365.747
XS GIS Cut Line= 4
     1729363.979      307645.619     1729526.017      307339.188
     1729663.575      307203.800     1730028.503      306837.433
#Sta/Elev= 30
       0 1006.86    27.6 1009.78    41.0 1010.12   182.0 1005.89   247.9  994.30
   282.7  984.40   309.6  977.69   350.7  968.78   369.8  965.47   386.6  963.69
   403.4  963.04   455.2  963.76   486.2  962.88   503.1  960.89   519.4  956.95
   534.4  955.36   536.9  955.17   562.9  964.24   572.1  966.23   605.8  970.29
   621.7  974.02   671.0  988.91   688.8  993.19   754.8 1003.67   771.6 1007.19
   823.2 1020.02   898.7 1040.20   922.4 1048.54   957.5 1062.88  1056.7 1106.15
#Mann= 3 , 0 , 0
       0     0.1       0   519.4   0.045       0   534.4     0.1       0
Bank Sta=   519.4,   534.4
Exp/Cntr=0.3,0.1

Type RM Length L Ch R = 1 ,7329.7,411.9,405.42,398.74
XS GIS Cut Line= 3
     1729675.976      307816.608     1729973.115      307387.815
     1730268.550      306999.617
#Sta/Elev= 30
       0 1034.19    49.9 1022.44    64.3 1020.11    81.0 1018.48   113.8 1017.37
   185.2 1005.63   224.7  999.91   247.8  993.53   295.5  975.65   324.4  967.36
   338.8  964.64   395.4  959.91   480.7  954.68   495.9  952.60   506.3  951.33
   510.9  951.60   514.8  952.13   556.6  962.88   650.4  994.17   661.0  997.22
   705.8 1005.01   765.5 1011.28   780.4 1013.39   795.3 1016.15   825.1 1024.00
   840.1 1029.40   869.9 1043.79   938.5 1073.50   980.9 1094.06  1009.5 1109.07
#Mann= 3 , 0 , 0
       0     0.1       0   495.9   0.045       0   510.9     0.1       0
Bank Sta=   495.9,   510.9
Exp/Cntr=0.3,0.1

Type RM Length L Ch R = 1 ,6924.3,448.646,451.403,459.536
XS GIS Cut Line= 3
     1730003.436      308119.076     1730165.609      307648.943
     1730337.528      307053.298
#Sta/Elev= 30
       0 1024.00    36.8 1017.90   142.3 1010.24   212.6 1000.10   266.0  996.21
   288.0  994.06   329.0  987.32   338.2  986.52   350.8  984.48   375.7  977.37
   401.0  972.23   413.6  968.81   462.3  951.80   476.4  949.69   477.3  949.73
   583.4  955.15   612.2  957.57   625.0  959.34   631.4  960.63   662.1  969.72
   756.0  995.32   785.6  999.46   835.1 1007.98   896.9 1020.07   933.9 1028.02
   946.3 1031.31   958.6 1035.62  1005.4 1053.87  1069.9 1080.51  1117.2 1101.71
#Mann= 3 , 0 , 0
       0     0.1       0   462.3   0.045       0   477.3     0.1       0
Bank Sta=   462.3,   477.3
Exp/Cntr=0.3,0.1

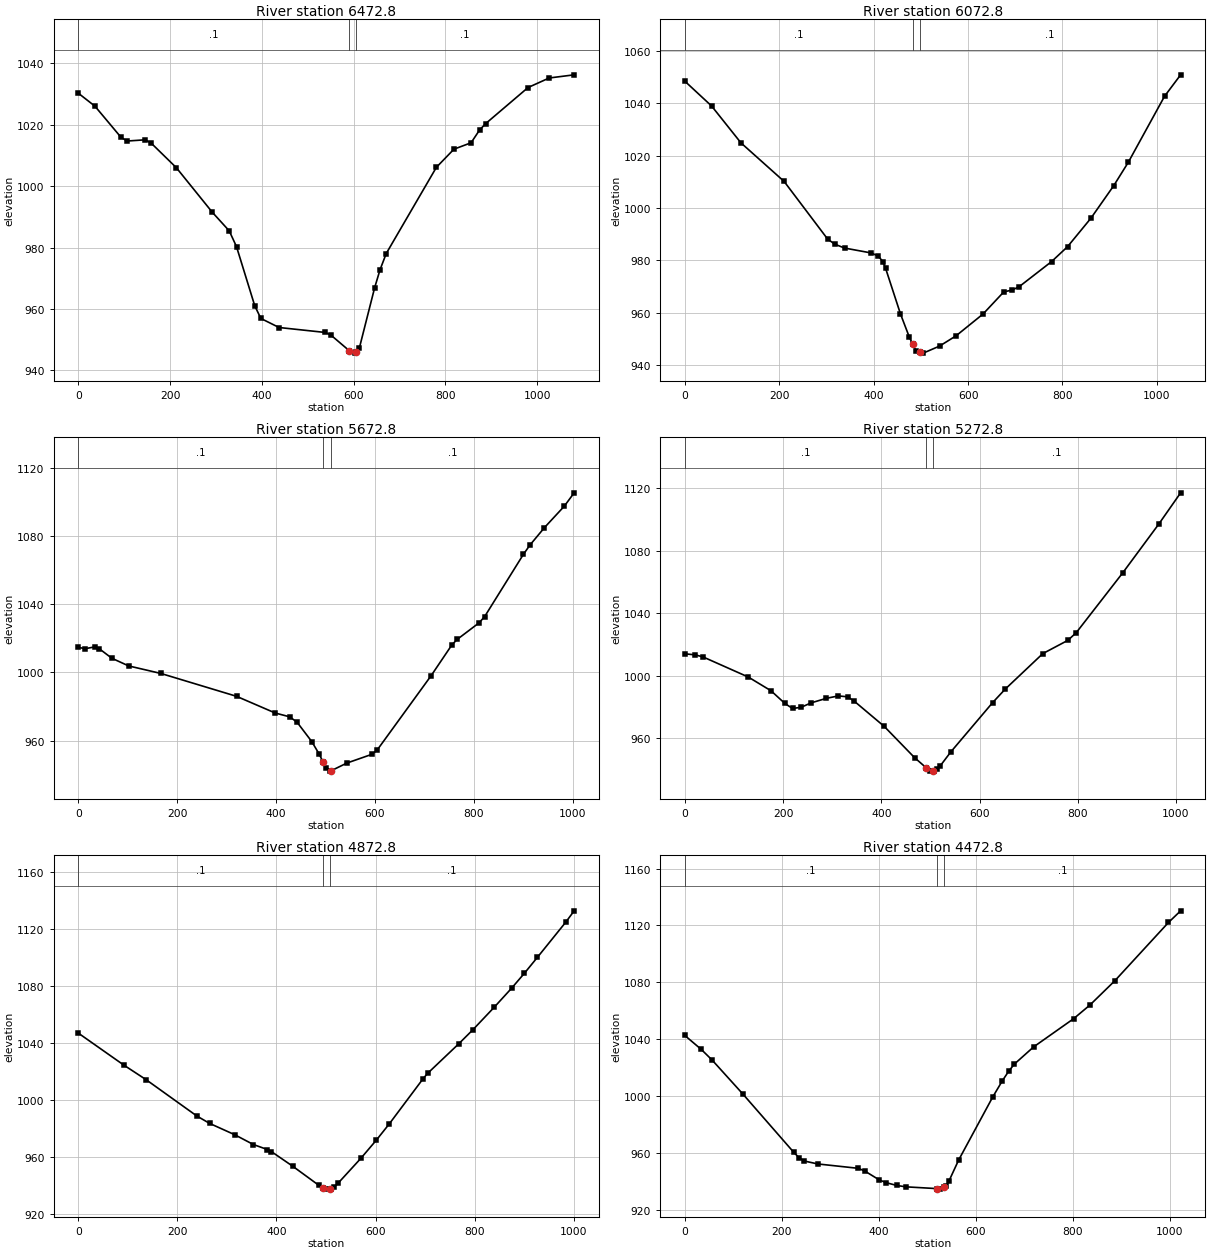
Type RM Length L Ch R = 1 ,6472.8,390.258,400,399.942
XS GIS Cut Line= 3
     1730267.792      308191.663     1730532.017      307655.383
     1730838.573      307281.843
#Sta/Elev= 30
       0 1030.29    36.2 1026.06    93.2 1015.88   106.5 1014.71   146.2 1015.11
   159.4 1013.93   213.6 1006.01   291.8  991.52   328.8  985.44   344.7  980.28
   384.4  961.03   397.7  956.90   437.4  953.95   538.3  952.33   550.5  951.46
   590.3  946.40   603.4  945.60   605.3  945.90   612.5  947.35   645.6  966.88
   657.4  972.77   670.9  978.05   780.2 1006.14   818.4 1012.05   855.8 1014.14
   874.5 1018.34   887.7 1020.40   979.9 1032.14  1026.0 1035.25  1080.4 1036.28
#Mann= 3 , 0 , 0
       0     0.1       0   590.3   0.045       0   605.3     0.1       0
Bank Sta=   590.3,   605.3
Exp/Cntr=0.3,0.1

Type RM Length L Ch R = 1 ,6072.8,405.481,400,398.8
XS GIS Cut Line= 3
     1730366.812      308290.989     1730745.496      307980.211
     1731101.423      307547.403
#Sta/Elev= 30
       0 1048.50    56.8 1039.00   119.0 1024.91   210.4 1010.18   302.6  988.14
   317.9  986.19   338.4  984.73   394.7  982.86   410.1  981.64   419.4  979.55
   425.4  976.94   456.8  959.57   475.6  950.68   482.4  948.14   490.2  945.35
   497.4  944.83   504.9  944.58   539.6  947.27   574.6  951.20   631.8  959.54
   675.8  968.01   693.3  968.66   708.7  970.03   777.0  979.58   810.7  985.26
   860.1  996.11   908.5 1008.56   939.3 1017.48  1016.1 1042.71  1050.2 1050.92
#Mann= 3 , 0 , 0
       0     0.1       0   482.4   0.045       0   497.4     0.1       0
Bank Sta=   482.4,   497.4
Exp/Cntr=0.3,0.1

Type RM Length L Ch R = 1 ,5672.8,398.82,400,399.727
XS GIS Cut Line= 3
     1730802.178      308535.023     1731101.158      308131.076
     1731396.129      307727.184
#Sta/Elev= 30
       0 1014.68    14.3 1013.97    33.9 1015.02    42.4 1013.89    67.9 1008.31
   101.8 1003.82   166.8  999.41   319.9  985.99   398.3  976.17   427.8  973.92
   442.6  970.69   472.1  959.41   486.9  952.16   495.1  947.35   500.8  944.06
   509.3  942.08   510.1  942.15   543.2  946.83   594.2  952.00   604.6  954.57
   713.2  997.99   755.7 1016.28   766.3 1019.42   810.4 1029.11   821.6 1032.74
   900.1 1069.32   913.3 1074.76   942.7 1085.02   982.6 1097.52  1002.7 1105.41
#Mann= 3 , 0 , 0
       0     0.1       0   495.1   0.045       0   510.1     0.1       0
Bank Sta=   495.1,   510.1
Exp/Cntr=0.3,0.1

Type RM Length L Ch R = 1 ,5272.8,406.39,400,395.448
XS GIS Cut Line= 3
     1731114.281      308730.281     1731431.304      308345.313
     1731727.222      307929.102
#Sta/Elev= 30
       0 1014.14    21.7 1013.42    37.1 1012.13   129.4  999.23   175.5  990.46
   203.7  982.35   219.3  979.11   237.0  979.90   256.7  982.66   288.1  985.61
   312.7  987.17   331.4  986.59   344.7  983.86   406.1  967.61   467.7  947.65
   491.2  941.21   498.9  939.26   506.2  939.04   507.4  939.00   513.1  940.08
   520.0  942.37   541.5  951.28   626.6  982.85   652.2  991.48   728.8 1014.25
   779.9 1022.76   796.9 1027.66   891.8 1066.07   964.7 1097.10  1009.4 1117.21
#Mann= 3 , 0 , 0
       0     0.1       0   491.2   0.045       0   506.2     0.1       0
Bank Sta=   491.2,   506.2
Exp/Cntr=0.3,0.1

Type RM Length L Ch R = 1 ,4872.8,396.558,400,399.575
XS GIS Cut Line= 3
     1731590.538      308980.841     1731788.674      308521.191
     1731991.714      308063.732
#Sta/Elev= 30
       0 1046.79    91.6 1024.40   136.8 1014.11   239.4  988.57   265.2  983.39
   315.6  975.48   353.6  968.55   381.6  965.08   389.8  963.61   433.3  953.23
   485.0  940.09     493  938.37   498.7  937.27     508  937.39   510.9  937.43
   516.2  938.50   523.9  941.23   570.2  958.82   601.9  971.78   627.8  983.09
   696.1 1014.82   705.1 1018.52   768.1 1039.32   796.7 1049.21   840.1 1065.14
   874.6 1078.27   900.6 1088.83   926.6 1099.91   984.0 1124.66  1001.0 1132.64
#Mann= 3 , 0 , 0
       0     0.1       0     493   0.045       0     508     0.1       0
Bank Sta=     493,     508
Exp/Cntr=0.3,0.1

Type RM Length L Ch R = 1 ,4472.8,388.125,400,410.729
XS GIS Cut Line= 3
     1731888.699      309088.598     1732167.995      308641.589
     1732360.470      308184.666
#Sta/Elev= 30
       0 1042.63    34.0 1032.79    56.4 1025.31   120.3 1001.23   224.9  960.37
   235.6  956.67   246.3  954.32   274.3  952.24   358.3  949.15   372.3  947.06
   400.3  941.20   414.3  939.18   437.3  937.11   456.3  936.14   519.6  934.90
   526.3  934.53   534.6  935.96   539.2  936.79   544.6  939.97   565.0  955.02
   635.2  999.30   655.2 1010.79   668.0 1017.36   679.7 1022.42   719.6 1034.56
   802.1 1054.39   835.5 1063.93   887.0 1081.03   997.8 1122.09  1022.9 1130.29
#Mann= 3 , 0 , 0
       0     0.1       0   519.6   0.045       0   534.6     0.1       0
Bank Sta=   519.6,   534.6
Exp/Cntr=0.3,0.1

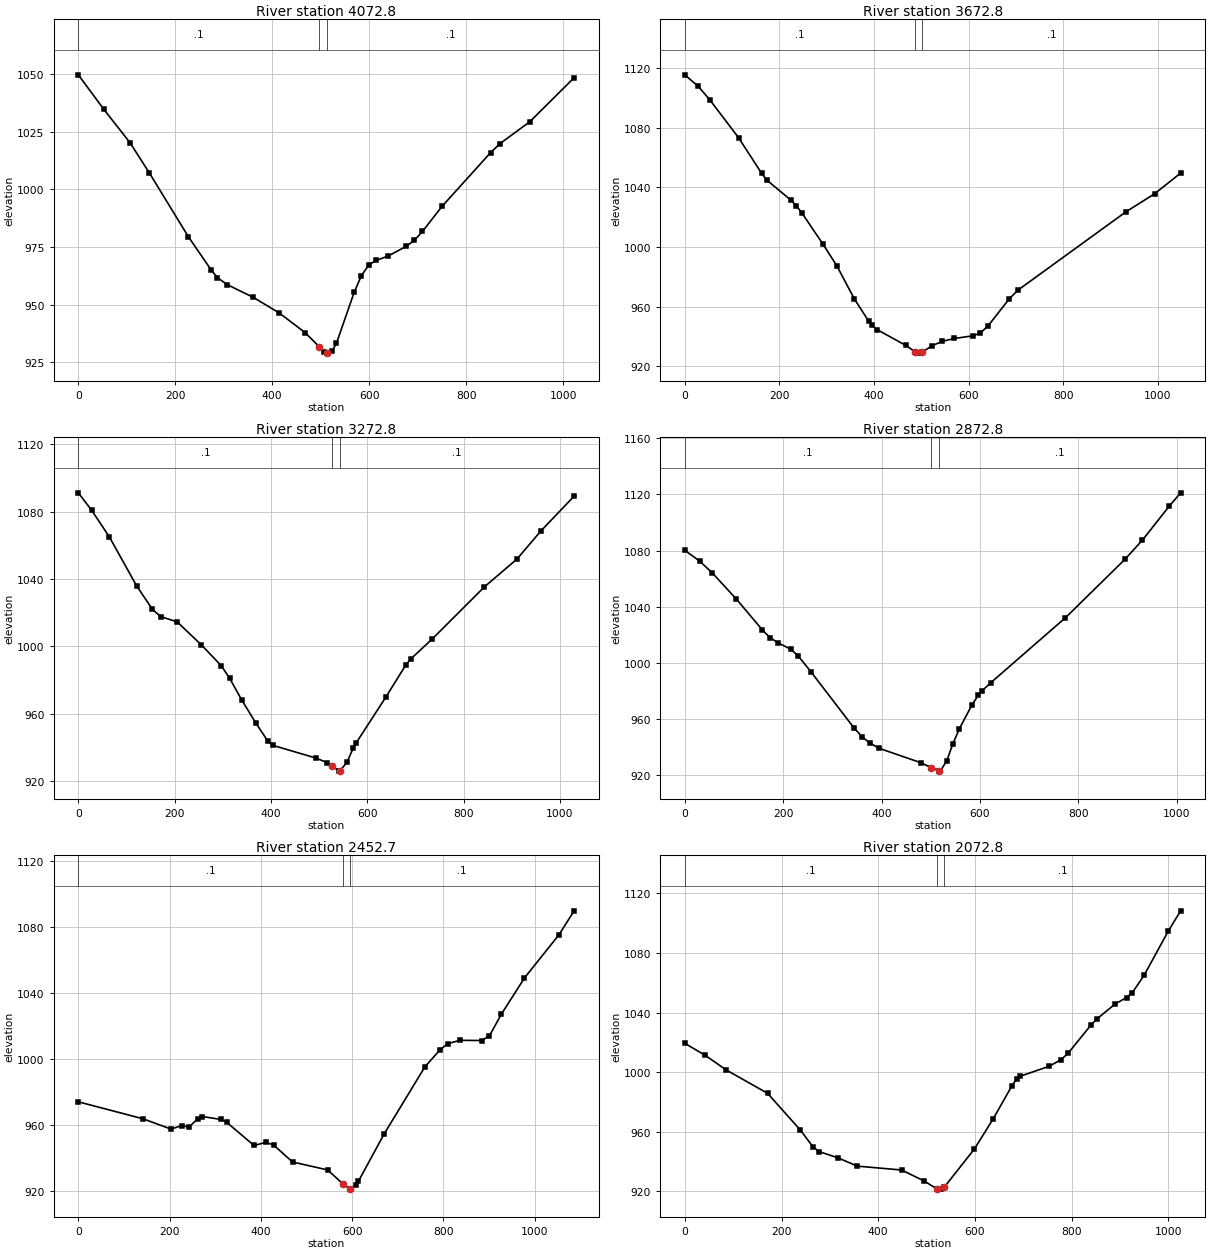
Type RM Length L Ch R = 1 ,4072.8,419.068,400,389.552
XS GIS Cut Line= 3
     1731966.849      309173.006     1732414.019      308939.449
     1732821.491      308618.882
#Sta/Elev= 30
       0 1049.65    52.7 1034.65   106.3 1020.30   146.2 1007.22   226.8  979.51
   274.4  964.90   287.1  961.67   307.2  958.66   360.8  953.16   414.3  946.41
   467.9  937.84     497  931.75   507.0  929.47     512  929.10   515.5  928.96
   523.7  929.95   532.4  933.15   569.0  955.29   584.1  962.62   600.0  967.37
   614.3  969.14   639.4  971.10   676.1  975.24   693.0  977.85   709.9  981.71
   750.3  992.60   850.7 1015.96   869.9 1019.82   931.5 1029.32  1022.9 1048.41
#Mann= 3 , 0 , 0
       0     0.1       0     497   0.045       0     512     0.1       0
Bank Sta=     497,     512
Exp/Cntr=0.3,0.1

Type RM Length L Ch R = 1 ,3672.8,389.387,400,414.646
XS GIS Cut Line= 3
     1732566.710      309678.579     1732686.355      309198.419
     1732905.030      308689.762
#Sta/Elev= 30
       0 1115.33    27.9 1107.75    52.4 1098.78   113.6 1073.26   162.5 1049.33
   173.3 1044.84   223.7 1031.53   235.9 1027.67   248.2 1022.50   291.3 1002.29
   321.6  987.31   358.3  965.30   388.8  950.29   395.0  947.80   407.2  944.50
   467.1  934.07   487.3  929.68   492.9  928.85   502.3  929.62   523.5  933.90
   544.5  936.73   570.3  938.70   609.1  940.44   625.0  942.30   641.0  946.98
   686.6  965.42   704.3  971.01   932.2 1023.39   993.5 1035.64  1048.5 1049.49
#Mann= 3 , 0 , 0
       0     0.1       0   487.3   0.045       0   502.3     0.1       0
Bank Sta=   487.3,   502.3
Exp/Cntr=0.3,0.1

Type RM Length L Ch R = 1 ,3272.8,394.561,400,402.316
XS GIS Cut Line= 3
     1732659.111      309731.780     1733015.077      309331.934
     1733447.011      309091.341
#Sta/Elev= 30
       0 1091.24    28.0 1080.74    64.7 1064.91   121.0 1035.94   154.0 1021.92
   171.1 1017.63   205.1 1014.53   255.6 1000.81   296.9  988.44   314.2  980.99
   339.7  967.89   368.3  954.52   393.6  943.55   404.0  941.06   493.3  933.53
   516.3  930.84   527.8  928.56   541.7  925.74   542.8  925.76   557.7  930.91
   571.3  939.59   576.6  942.32   639.2  969.99   680.0  988.80   690.1  992.36
   734.3 1004.12   843.1 1035.23   911.0 1051.86   960.7 1068.55  1029.8 1089.29
#Mann= 3 , 0 , 0
       0     0.1       0   527.8   0.045       0   542.8     0.1       0
Bank Sta=   527.8,   542.8
Exp/Cntr=0.3,0.1

Type RM Length L Ch R = 1 ,2872.8,424.139,420.181,411.482
XS GIS Cut Line= 3
     1732834.315      309929.884     1733250.466      309637.062
     1733709.176      309440.561
#Sta/Elev= 30
       0 1080.27    29.9 1072.62    56.2 1064.03   105.0 1045.46   157.8 1023.54
   173.1 1018.10   190.2 1014.28   215.6 1009.80   230.4 1005.14   256.9  993.56
   343.6  953.97   361.0  947.34   375.5  943.23   394.7  939.34   479.9  929.06
   501.3  925.48   516.3  923.43   519.4  923.07   532.6  930.55   545.2  942.71
   558.2  953.31   584.0  970.33   596.9  977.26   604.7  980.40   622.5  986.15
   773.8 1032.25   894.4 1073.70   930.3 1087.51   984.8 1111.68  1007.9 1121.15
#Mann= 3 , 0 , 0
       0     0.1       0   501.3   0.045       0   516.3     0.1       0
Bank Sta=   501.3,   516.3
Exp/Cntr=0.3,0.1

Type RM Length L Ch R = 1 ,2452.7,388.731,379.819,368.034
XS GIS Cut Line= 4
     1733239.280      310514.334     1733324.970      310138.927
     1733458.355      310003.603     1733818.310      309639.738
#Sta/Elev= 30
       0  974.06   142.2  963.75   203.1  957.53   227.4  959.71   242.3  958.72
   262.1  963.95   272.0  965.13   312.7  963.37   324.9  961.70   385.1  947.60
   411.1  949.50   428.1  947.87   469.4  937.59   546.4  932.79   580.5  924.16
   595.5  921.16   597.1  921.15   608.4  923.51   614.0  925.97   669.6  954.29
   759.5  995.22   793.1 1005.72   809.9 1009.33   836.6 1011.34   884.1 1011.20
   901.0 1014.05   927.4 1027.28   977.8 1049.14  1053.0 1075.16  1086.7 1089.81
#Mann= 3 , 0 , 0
       0     0.1       0   580.5   0.045       0   595.5     0.1       0
Bank Sta=   580.5,   595.5
Exp/Cntr=0.3,0.1

Type RM Length L Ch R = 1 ,2072.8,390.236,400,409.437
XS GIS Cut Line= 3
     1733588.804      310645.416     1733783.926      310154.184
     1733910.504      309673.806
#Sta/Elev= 30
       0 1019.39    42.5 1011.29    85.8 1001.50   171.1  985.88   239.1  961.17
   264.7  950.11   277.4  946.81   315.8  942.69   356.9  937.02   448.4  934.41
   494.6  927.10   521.1  921.79   530.8  921.59   536.1  922.71   598.8  948.51
   637.7  968.73   676.5  990.95   686.3  995.58   692.4  997.18   753.8 1004.05
   778.3 1008.53   793.1 1012.91   839.7 1031.59   852.0 1035.71   890.3 1045.93
   913.4 1050.07   925.7 1053.48   950.2 1065.29   999.3 1094.43  1025.3 1108.29
#Mann= 3 , 0 , 0
       0     0.1       0   521.1   0.045       0   536.1     0.1       0
Bank Sta=   521.1,   536.1
Exp/Cntr=0.3,0.1