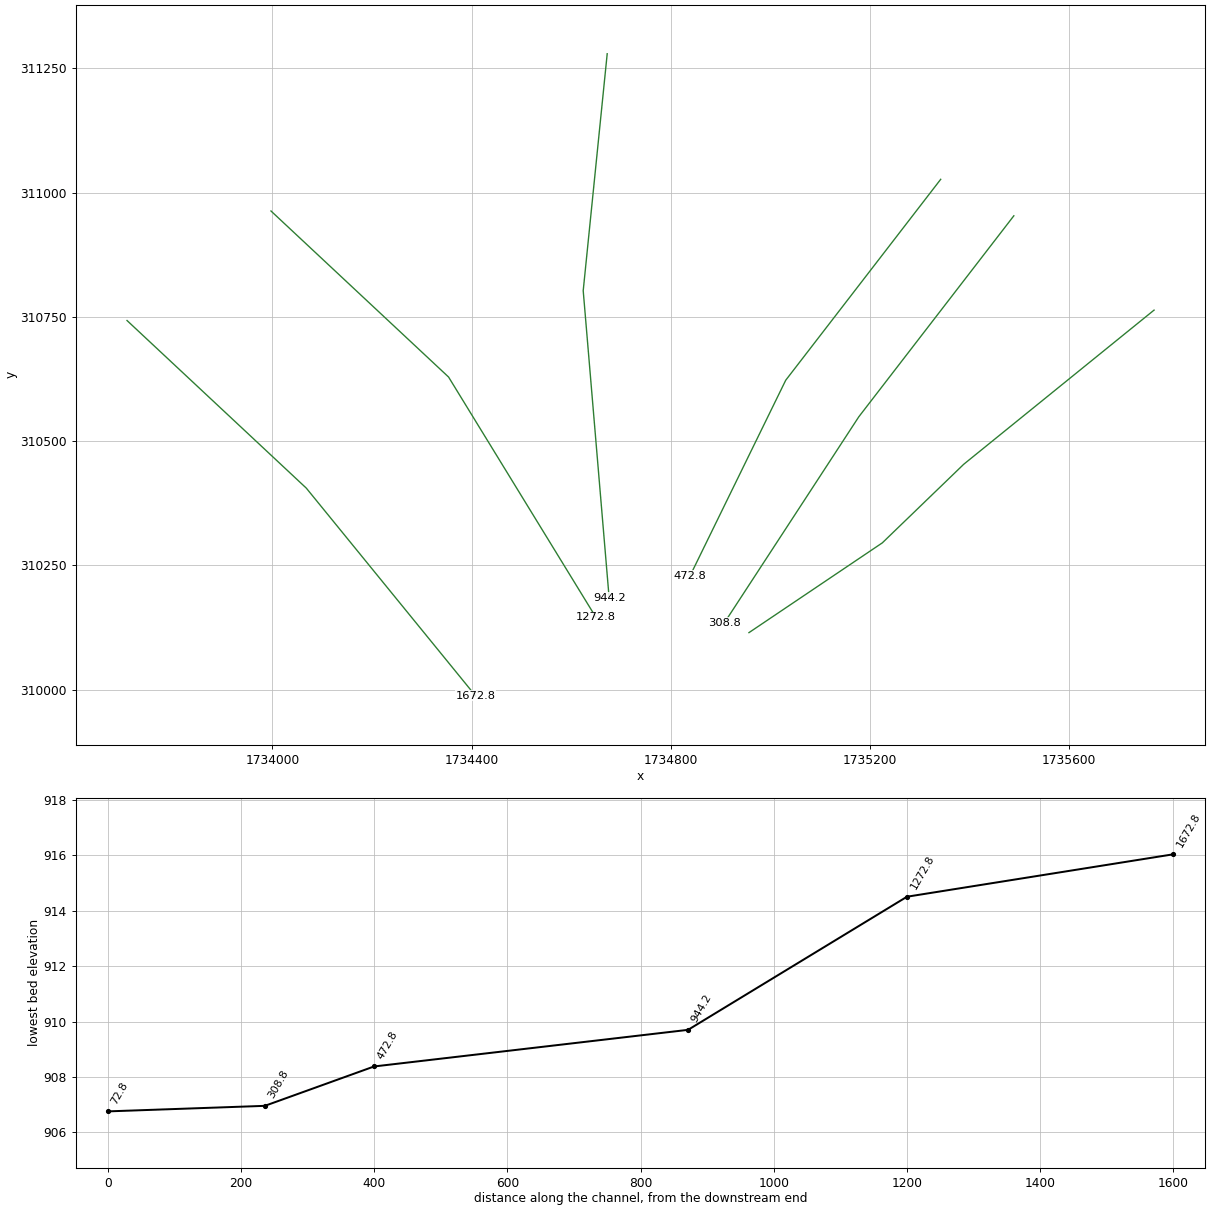
HEC-RAS study LambertRn.prj: LambertRn

--- LambertRn.g01 (geometry) --- (continued)

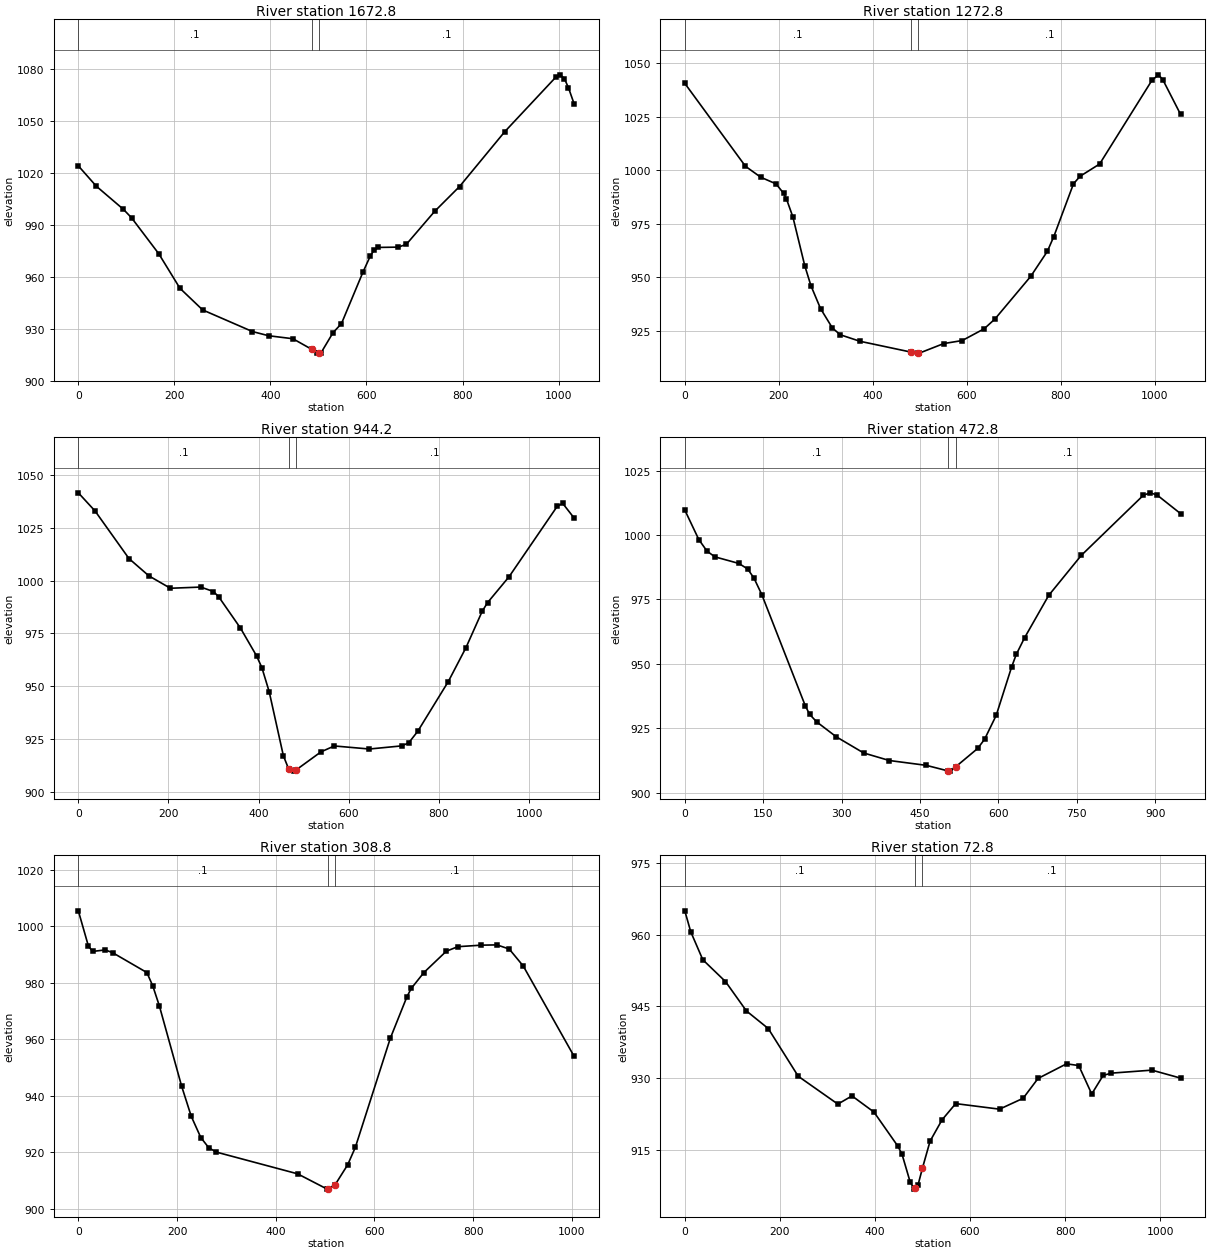
Type RM Length L Ch R = 1 ,1672.8,400.168,400,396.112
XS GIS Cut Line= 3
     1733707.847      310742.551     1734068.004      310405.227
     1734408.082      309987.117
#Sta/Elev= 30
       0 1024.27    37.3 1012.55    94.0  999.10   110.8  994.25   167.4  973.50
   211.6  953.50   258.8  941.01   362.6  928.49   396.4  926.07   446.8  924.35
     486  918.22   497.2  916.03     501  916.27   505.7  916.38   530.3  927.84
   547.9  933.10   592.7  962.89   608.0  972.21   615.4  975.39   624.4  977.12
   666.0  977.29   682.9  978.89   742.0  997.99   793.7 1012.32   887.8 1043.99
   995.2 1075.83  1003.6 1076.88  1012.0 1074.73  1020.5 1069.44  1032.4 1060.04
#Mann= 3 , 0 , 0
       0     0.1       0     486   0.045       0     501     0.1       0
Bank Sta=     486,     501
Exp/Cntr=0.3,0.1

Type RM Length L Ch R = 1 ,1272.8,349.48,328.658,318.117
XS GIS Cut Line= 3
     1733997.047      310962.930     1734353.774      310628.819
     1734649.579      310145.532
#Sta/Elev= 30
       0 1040.65   129.1 1001.88   161.6  996.76   194.1  993.66   210.4  989.22
   216.4  986.60   230.1  978.16   255.3  955.42   268.5  946.03   288.9  935.34
   314.1  926.28   330.9  923.09   372.7  920.05   481.3  914.99   496.3  914.52
   499.2  914.50   551.0  918.96   590.6  920.39   637.3  925.90   660.2  930.47
   736.4  950.42   771.6  962.05   785.5  969.03   827.3  993.66   841.2  997.18
   883.0 1002.94   994.3 1042.06  1008.2 1044.64  1017.3 1042.45  1055.4 1026.10
#Mann= 3 , 0 , 0
       0     0.1       0   481.3   0.045       0   496.3     0.1       0
Bank Sta=   481.3,   496.3
Exp/Cntr=0.3,0.1

Type RM Length L Ch R = 1 ,944.2,483.83,471.342,460.038
XS GIS Cut Line= 3
     1734672.446      311279.372     1734624.234      310802.550
     1734676.337      310184.224
#Sta/Elev= 30
       0 1041.72    37.2 1033.08   112.3 1010.54   156.5 1002.33   204.2  996.45
   271.6  997.01   299.7  994.90   311.6  992.33   359.4  977.63   395.2  964.43
   407.1  958.82   423.4  947.33   454.8  917.00   466.8  910.56   478.7  909.70
   481.8  910.07   538.2  918.84   567.8  921.64   645.5  920.19   717.0  921.67
   732.7  923.09   752.7  928.54   820.6  952.18   859.9  968.32   895.7  985.47
   907.6  989.61   955.3 1001.89  1062.3 1035.34  1074.4 1036.71  1099.8 1029.74
#Mann= 3 , 0 , 0
       0     0.1       0   466.8   0.045       0   481.8     0.1       0
Bank Sta=   466.8,   481.8
Exp/Cntr=0.3,0.1

Type RM Length L Ch R = 1 ,472.8,163.913,164.041,161.247
XS GIS Cut Line= 3
     1735342.371      311026.721     1735030.978      310622.283
     1734838.839      310228.698
#Sta/Elev= 30
       0 1009.73    26.8  998.26    42.5  993.78    57.4  991.56   103.4  988.99
   120.3  986.84   132.4  983.26   147.3  976.90   230.4  933.78   238.8  930.41
   252.2  927.51   289.6  921.72   342.1  915.43   391.2  912.50   462.0  910.62
   502.9  908.49   507.0  908.38   517.9  910.01   560.2  917.18   573.4  920.74
   595.7  930.05   625.1  948.79   634.0  953.67   649.8  960.10   696.1  976.60
   758.4  992.12   877.3 1015.49   890.5 1016.40   903.7 1015.50   948.4 1008.31
#Mann= 3 , 0 , 0
       0     0.1       0   502.9   0.045       0   517.9     0.1       0
Bank Sta=   502.9,   517.9
Exp/Cntr=0.3,0.1

Type RM Length L Ch R = 1 ,308.8,241.368,235.959,230.915
XS GIS Cut Line= 3
     1735489.269      310953.272     1735177.876      310548.833
     1734908.208      310134.847
#Sta/Elev= 30
       0 1005.50    20.3  993.08    28.8  991.12    54.6  991.66    69.6  990.67
   138.8  983.65   150.8  978.93   164.2  971.82   209.2  943.45   228.7  932.77
   248.1  925.23   264.4  921.58   279.4  920.08   444.2  912.38   504.2  906.96
   505.1  906.99   520.1  908.48   545.7  915.58   561.2  921.76   632.0  960.36
   665.8  975.11   674.5  978.03   700.1  983.65   745.4  991.19   768.7  992.80
   816.2  993.34   848.1  993.44   872.9  991.98   901.3  985.98  1004.5  953.94
#Mann= 3 , 0 , 0
       0     0.1       0   505.1   0.045       0   520.1     0.1       0
Bank Sta=   505.1,   520.1
Exp/Cntr=0.3,0.1

Type RM Length L Ch R = 1 ,72.8,79.611,72.85,64.084
XS GIS Cut Line= 4
     1735770.958      310763.482     1735388.772      310453.403
     1735225.111      310295.132     1734957.174      310114.444
#Sta/Elev= 30
       0  964.95    12.5  960.57    37.9  954.72    85.6  950.16   129.6  944.02
   175.5  940.34   238.6  930.36   321.9  924.54   351.7  926.25   397.9  922.87
   448.5  915.69   457.0  914.02   473.8  908.32   482.3  906.76   484.7  906.98
   490.7  907.67   499.7  911.10   515.9  916.79   541.1  921.25   569.8  924.64
   662.0  923.48   711.6  925.75   743.0  929.90   802.9  932.96   828.6  932.60
   855.9  926.65   879.9  930.53   897.0  931.01   982.5  931.64  1042.9  929.97
#Mann= 3 , 0 , 0
       0     0.1       0   484.7   0.045       0   499.7     0.1       0
Bank Sta=   484.7,   499.7
Exp/Cntr=0.3,0.1